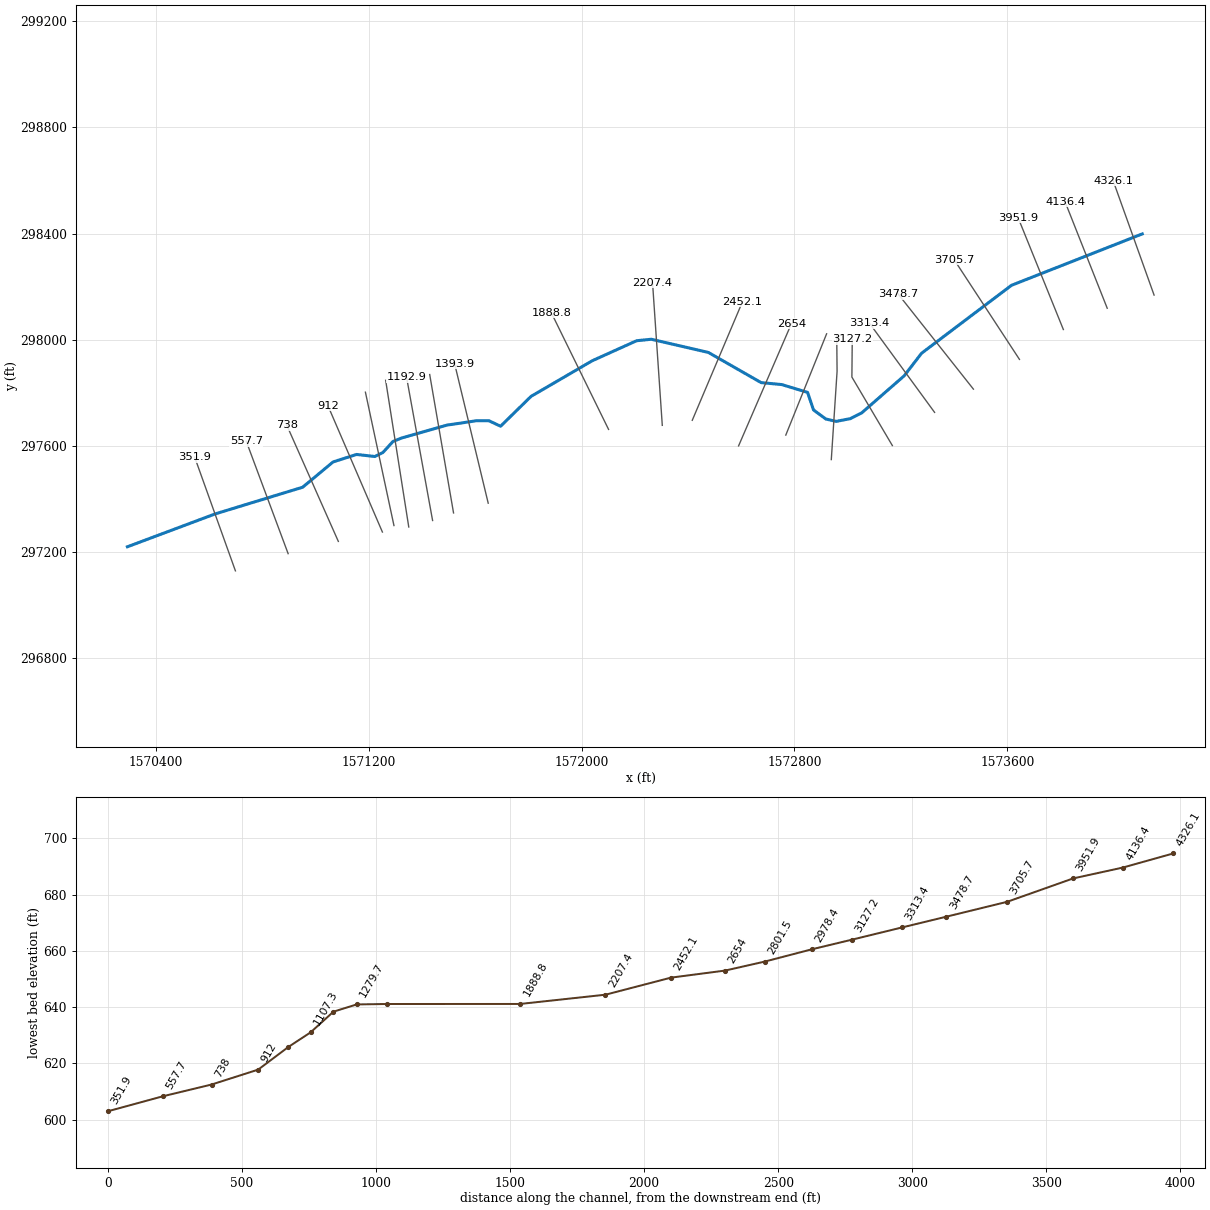
--- prslybgbrn.prj (project) ---

Proj Title=prslybgbrn
Current Plan=p01
Default Exp/Contr=0,0
English Units
Geom File=g01
Flow File=f01
Plan File=p01
BEGIN DESCRIPTION:
END DESCRIPTION:
DSS Export Rating Curves= 0
DSS Export Rating Curve Sorted= 0
DSS Export Volume Flow Curves= 0
DXF OffsetX= 0
DXF OffsetY= 0
DXF ScaleX= 0
DXF ScaleY= 0

--- prslybgbrn.p01 (plan) ---

Plan Title=Approximate Study  - 100yr
Program Version=4.00
Geom File=g01
Flow File=f01
Subcritical Flow
K Sum by GR= 0
Std Step Tol= 0.01
Critical Tol= 0.01
Num of Std Step Trials= 20
Max Error Tol= 0.3
Flow Tol Ratio= 0.001
Split Flow NTrial= 30
Split Flow Tol= 0.02
Split Flow Ratio= 0.02
Log Output Level= 0
Friction Slope Method= 1
Unsteady Friction Slope Method= 2
Unsteady Bridges Friction Slope Method= 1
Parabolic Critical Depth
Global Vel Dist= 0 , 0 , 0
Global Log Level= 0
CheckData=True
Encroach Param=-1 ,0,0, 0
Run HTab= 0
Run UNet= 0
Run PostProcess= 0
Run WQNet= 0
UNET Theta= 0
UNET Theta Warmup= 0
UNET ZTol= 0
UNET ZSATol= 0
UNET MxIter= 0
UNET MaxInSteps= 0
UNET DtIC= 0
UNET DtMin= 0
UNET MaxCRTS= 0
UNET WFStab= 0
UNET SFStab= 0
UNET WFX= 1
UNET SFX= 1
UNET DSS MLevel= 1
UNET DZMax Abort= 0
UNET Convert EG Bridges= 0
UNET Use Existing IB Tables= 0
UNET Froude Reduction=False
UNET Froude Limit= 0
UNET Froude Power= 0
UNET Time Slicing=0,0, 5
Write IC File= 0
Echo Input=False
Echo Output=False
Write Detailed= 0
Detailed Automatic Start=False, 0
WQ ULTIMATE=-1
WQ Max Comp Step=1HOUR
WQ Output Interval=15MIN
WQ Output Selected Increments= 0
WQ Output face flow=0
WQ Output face velocity=0
WQ Output face area=0
WQ Output face dispersion=0
WQ Output cell volume=0
WQ Output cell surface area=0
WQ Output cell continuity=0
WQ Output face conc=0
WQ Output face dconc_dx=0
WQ Output face courant=0
WQ Output face peclet=0
WQ Output face adv mass=0
WQ Output face disp mass=0
WQ Output cell mass=0
WQ Output cell source sink temp=0
WQ Output cell source sink nsm=0
WQ Output MaxMinRange=-1
WQ Daily Max Min Mean=-1
WQ Daily Range=0
WQ Daily Time=0
WQ Create Restart=0
WQ Fixed Restart=0
WQ System Summary=False
Sorting and Armoring Iterations= 10
XS Update Threshold= 0.02
Hydraulics Update Threshold= 0.02
Energy Slope Method= 1
Volume Change Method= 0
XS Weighting Method= 0
Number of US Weighted Cross Sections= 1
Number of DS Weighted Cross Sections= 1
Upstream XS Weight=0.25
Main XS Weight=0.5
Downstream XS Weight=0.25
Number of DS XS's Weighted with US Boundary= 1
Upstream Boundary Weight= 1
Weight of XSs Associated with US Boundary= 0
Number of US XS's Weighted with DS Boundary= 1
Downstream Boundary Weight= 0.5
Weight of XSs Associated with DS Boundary= 0.5
Sediment Output Level= 4
Mass or Volume Output= 0
Output Increment Type= 1
Profile and TS Output Increment= 10
XS Output Flag= 0
XS Output Increment= 10
Disregard all LS=0
Disregard all Conn=0
Disregard all Breaches=0
Disregard all Pumps=0

--- prslybgbrn.f01 (steady flow) ---

Flow Title=USGS Regression Equation
Program Version=4.00
Number of Profiles= 1
Profile Names=P100yr
River Rch & RM=prslybgbrn,Main            ,4326.1
     371
River Rch & RM=prslybgbrn,Main            ,2654
     410
River Rch & RM=prslybgbrn,Main            ,1888.8
     455
Boundary for River Rch & Prof#=prslybgbrn,Main            , 1
Up Type= 0
Dn Type= 3
Dn Slope=0.02
DSS Import GetInterval= 0
DSS Import GetPeak= 0
DSS Import FillOption= 0

--- prslybgbrn.g01 (geometry) ---

Geom Title=USGS 3m DEM
Program Version=4.00

River Reach=prslybgbrn      ,Main
Reach XY= 30
     1574107.032      298398.802     1573615.689      298205.324
     1573277.571      297949.269     1573212.336      297864.398
     1573052.964      297725.058     1573009.773      297702.986
     1572956.052      297692.669     1572917.921      297701.595
     1572871.492      297735.736     1572849.125      297801.938
     1572752.109      297831.333     1572674.435       297838.83
     1572476.418      297952.256     1572261.914      298002.072
     1572206.567      297996.481     1572039.855      297921.112
     1571809.937      297787.036      1571695.27      297674.452
     1571651.405      297695.187     1571605.491      297695.318
      1571493.31      297678.545     1571323.068      297630.033
     1571290.811      297616.959     1571252.653      297575.157
     1571222.793       297560.46     1571153.839      297568.138
     1571065.607        297539.9     1570951.438      297444.772
     1570622.034       297343.99      1570292.53      297220.381

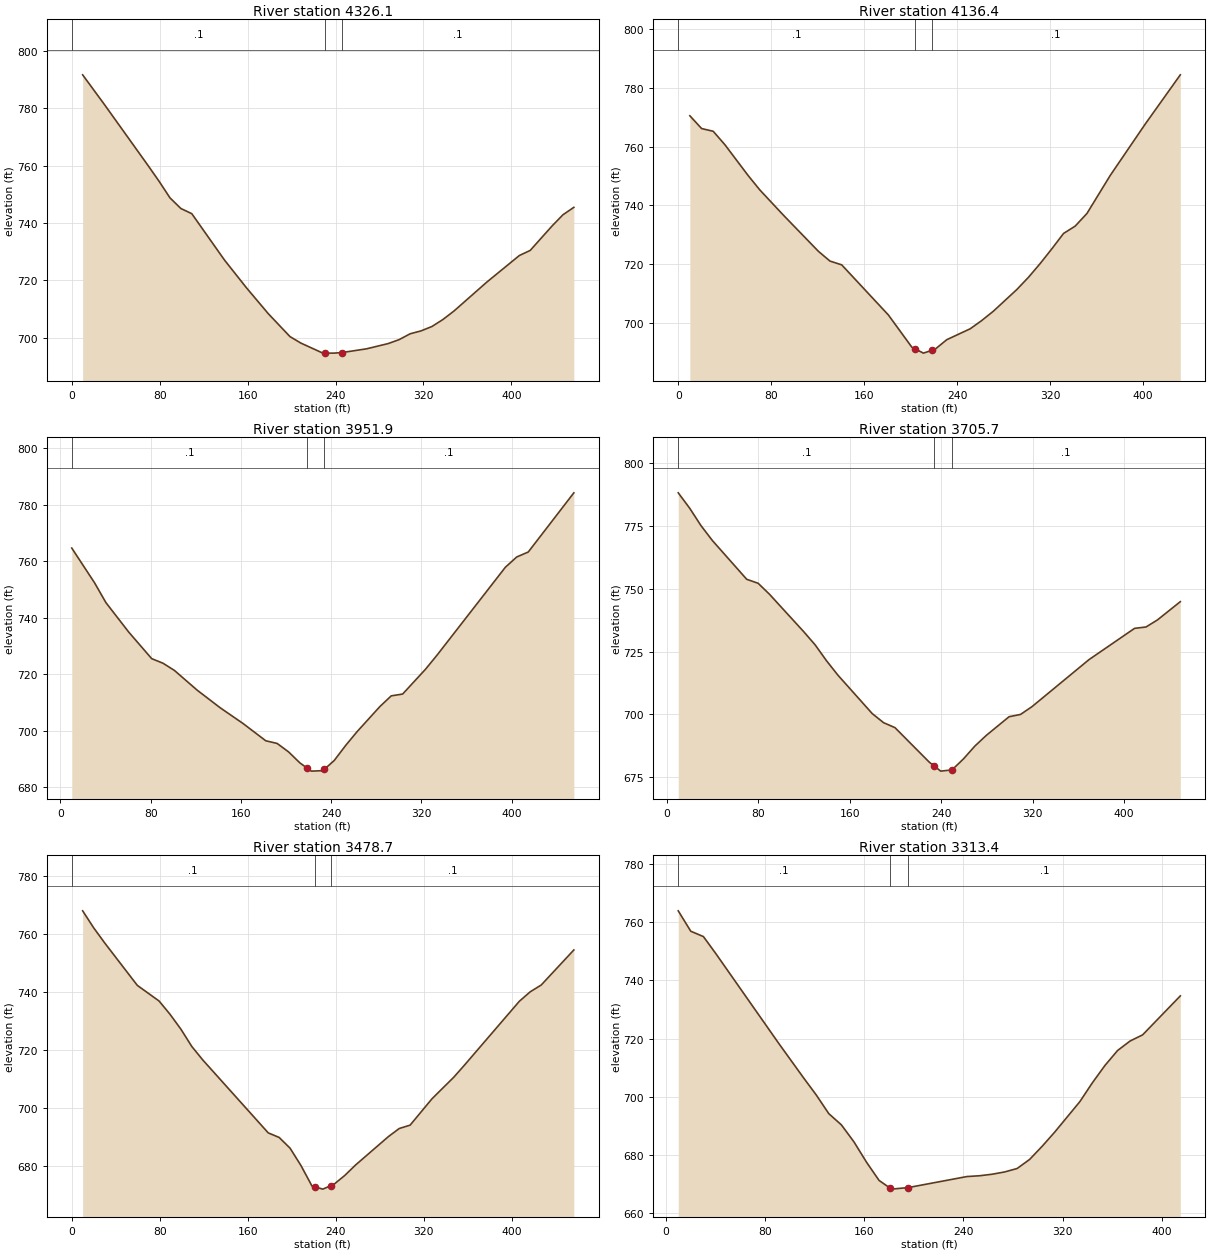
Type RM Length L Ch R = 1 ,4326.1  ,189,189.7,190.5
XS GIS Cut Line= 2
     1574151.555      298168.464     1573997.895      298598.665
#Sta/Elev= 30
     9.9  791.59    29.8   781.2    69.5  759.95    79.4  754.53    89.4  748.71
    99.3  745.01   109.2  743.22     139  727.04   158.9  717.42   178.8  708.38
   198.6  700.38   208.5  698.13   228.4  694.65   230.8  694.65   238.3  694.64
   245.8  694.83   268.1  696.13     288  697.98   297.9  699.35   307.9  701.38
   317.8  702.39   327.7  703.92   337.6  706.33   347.6  709.26   377.4  719.31
   407.2  728.64   417.1  730.42     437  738.94   446.9  742.84   456.8  745.43
#Mann= 3 , 0 , 0
       0      .1       0   230.8    .045       0   245.8      .1       0
Bank Sta=230.8,245.8
XS Rating Curve= 0 ,0
Exp/Cntr=0.3,0.1

Type RM Length L Ch R = 1 ,4136.4  ,184.3,184.5,184.7
XS GIS Cut Line= 2
     1573975.428      298118.918     1573816.608      298520.719
#Sta/Elev= 30
      10   770.5    20.1  766.15    30.1  765.22    40.2  760.62    60.3  750.06
    70.3  745.19    90.4  736.67   120.6  724.31   130.6  720.97   140.7  719.68
   180.9  702.58     201  691.64   203.5  691.12     211  689.59   218.5  690.57
     221  690.89   231.1  694.17   251.2  697.87   261.2   700.7   271.3  703.91
   291.4  711.27   301.4  715.43   311.5  720.13   321.5  725.13   331.6  730.38
   341.6  732.88   351.7  737.17   371.8  750.17   401.9  767.67   432.1  784.46
#Mann= 3 , 0 , 0
       0      .1       0   203.5    .045       0   218.5      .1       0
Bank Sta=203.5,218.5
XS Rating Curve= 0 ,0
Exp/Cntr=0.3,0.1

Type RM Length L Ch R = 1 ,3951.9  ,241.8,246.2,250.6
XS GIS Cut Line= 2
     1573810.564      298038.667       1573640.2      298460.569
#Sta/Elev= 30
    10.1  764.66    30.3  752.37    40.4  745.34    60.7  734.88    80.9  725.55
      91  723.91   101.1  721.36   121.3  714.37   141.6  708.17   161.8  702.62
     182  696.49   192.1  695.54   202.2  692.56   212.3  688.65   218.9 686.753
   222.4  685.75   232.6  685.92   233.9 686.385   242.7  689.53   252.8  694.83
   262.9   699.7   283.1  708.58   293.2  712.38   303.3  713.02   323.6  721.81
   333.7  726.74   394.3  757.86   404.4  761.51   414.6  763.26     455   784.2
#Mann= 3 , 0 , 0
    10.1      .1       0   218.9    .045       0   233.9      .1       0
Bank Sta=218.9,233.9
XS Rating Curve= 0 ,0
Exp/Cntr=0.3,0.1

Type RM Length L Ch R = 1 ,3705.7  ,225,227,229
XS GIS Cut Line= 2
     1573645.571      297926.162     1573399.875      298302.172
#Sta/Elev= 30
      10  788.21      20   782.1    29.9  775.16    39.9  769.21    69.9   753.8
    79.9  752.21    89.8  747.85   119.8  732.93   129.8  727.68   139.7  721.38
   149.7  715.63   179.7  700.34   189.6  696.73   199.6  694.75   229.6  681.01
   234.1 679.405   239.6  677.44   249.1  677.91   249.5  677.93   259.5   682.3
   269.5  687.42   279.5  691.67   299.4  699.09   309.4     700   319.4  703.08
   369.3  721.81   409.2  734.27   419.2  734.81   429.2  737.62   449.2  744.89
#Mann= 3 , 0 , 0
      10      .1       0   234.1    .045       0   249.1      .1       0
Bank Sta=234.1,249.1
XS Rating Curve= 0 ,0
Exp/Cntr=0.3,0.1

Type RM Length L Ch R = 1 ,3478.7  ,166.2,165.3,164.3
XS GIS Cut Line= 2
     1573472.498      297814.174     1573189.473      298172.537
#Sta/Elev= 30
     9.9  767.88    19.9  762.05    29.8  756.91    59.6  742.24    79.4  736.86
    89.3  732.32    99.3  727.14   109.2   721.2   119.1   716.6   178.7  691.49
   188.6  689.93   198.5  686.25   208.5  680.23   218.4  673.25   220.8  672.98
   228.3  672.15   235.8  673.36   238.3  673.76   248.2  676.83   258.1  680.45
   287.9   690.2   297.8     693   307.7  694.16   327.6  703.23   347.4  710.64
   357.4  714.92     407  736.75   416.9  740.02   426.9  742.35   456.6  754.42
#Mann= 3 , 0 , 0
       0      .1       0   220.8    .045       0   235.8      .1       0
Bank Sta=220.8,235.8
XS Rating Curve= 0 ,0
Exp/Cntr=0.3,0.1

Type RM Length L Ch R = 1 ,3313.4  ,188.4,186.2,184.1
XS GIS Cut Line= 2
     1573326.574      297726.619     1573082.235      298061.906
#Sta/Elev= 30
    10.1  763.88    20.2  756.88    30.4  755.04    40.5  749.14    91.1  718.39
   111.3  706.45   121.4  700.65   131.5  694.24   141.7  690.37   151.8  684.54
   161.9  677.58     172  671.33   180.6 668.776   182.1  668.33   195.6 668.869
   242.9  672.65     253  672.92   263.1  673.44   273.2  674.22   283.3   675.4
   293.4  678.52   303.6  683.08   313.7  687.94   333.9  698.36     344  704.84
   354.2  710.82   364.3  715.91   374.4  719.18   384.5  721.29   414.9  734.67
#Mann= 3 , 0 , 0
    10.1      .1       0   180.6    .045       0   195.6      .1       0
Bank Sta=180.6,195.6
XS Rating Curve= 0 ,0
Exp/Cntr=0.3,0.1

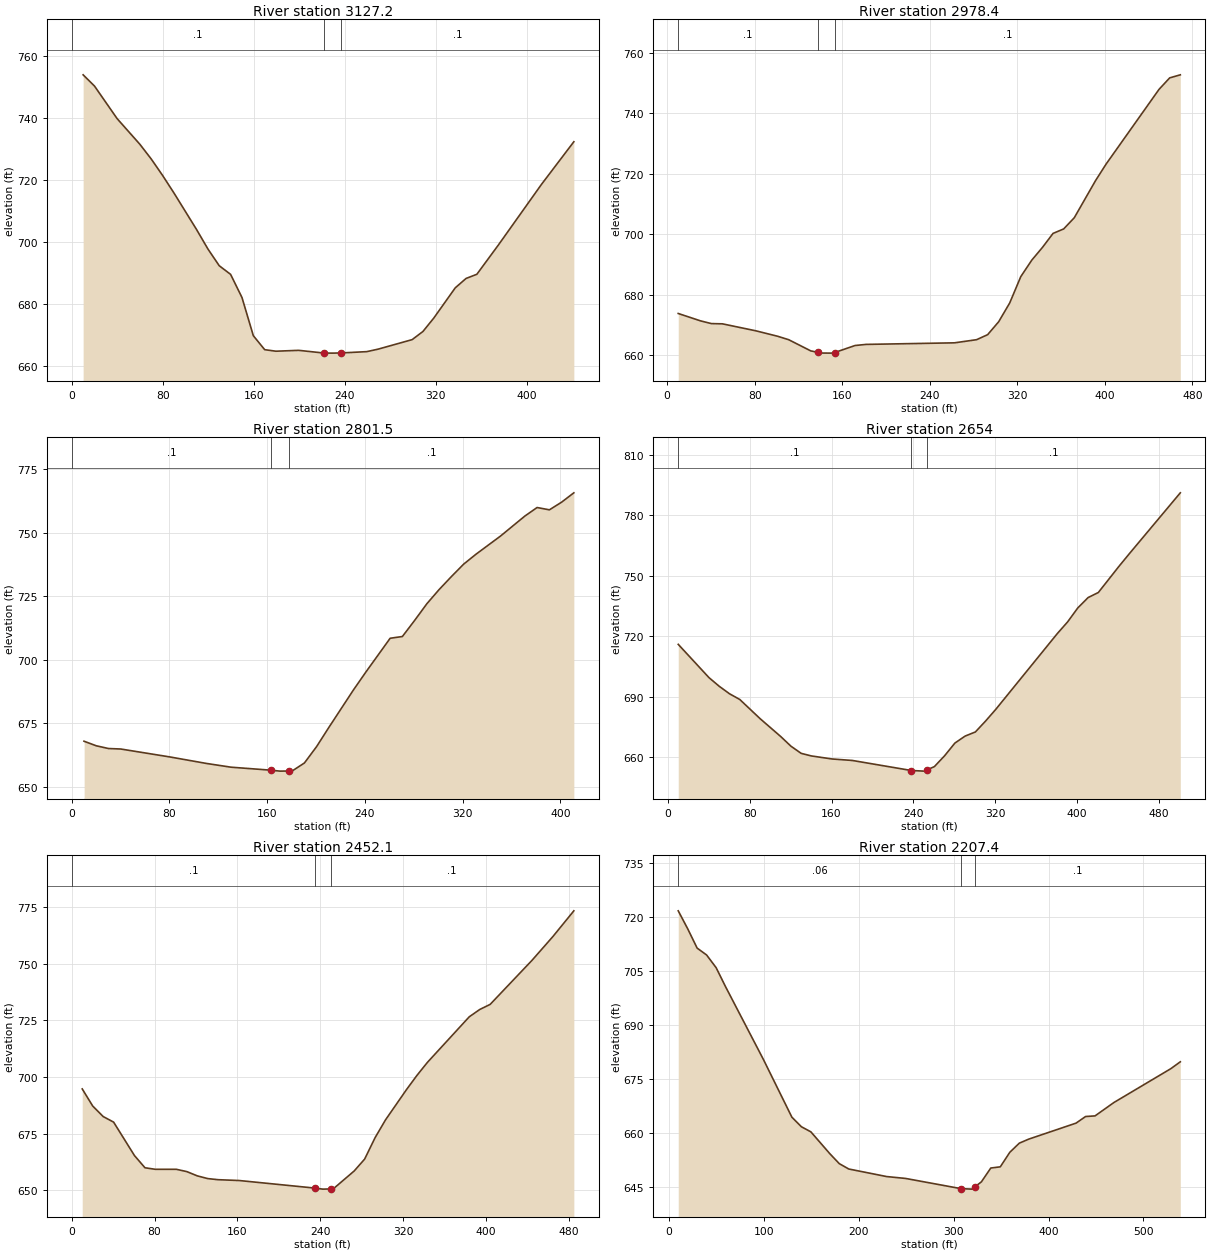
Type RM Length L Ch R = 1 ,3127.2  ,162.2,148.7,135.3
XS GIS Cut Line= 3
     1573167.754      297601.735     1573015.721      297859.648
     1573017.095      298001.891
#Sta/Elev= 30
      10  753.89      20  750.26    39.9  739.74    59.9  731.46    69.9   726.7
    79.8  721.44    89.8  715.77   109.8   703.9   119.8  697.61   129.7  692.23
   139.7  689.44   149.7  681.97   159.7  669.62   169.7  665.11   179.6  664.62
   199.6   664.9     222  664.02   229.5     664     237  664.06   259.5  664.48
   269.4  665.28   299.4  668.36   308.9     671   318.4  675.32   337.3  685.09
   346.8  688.12   356.3  689.47   375.3  698.96   413.2  718.54   441.6  732.28
#Mann= 3 , 0 , 0
       0      .1       0     222    .045       0     237      .1       0
Bank Sta=222,237
XS Rating Curve= 0 ,0
Exp/Cntr=0.3,0.1

Type RM Length L Ch R = 1 ,2978.4  ,181.8,176.9,170.7
XS GIS Cut Line= 3
     1572938.347      297548.795     1572960.066      297881.367
     1572958.709       298017.11
#Sta/Elev= 30
    10.1  673.73    30.3   671.3    40.4  670.38    50.5   670.3    80.8  668.01
     101  666.18   111.1  665.04   131.3  661.33     138 660.866   141.4  660.63
   151.5   660.6     153  660.79   171.7  663.12   181.8  663.49   262.6  664.01
   282.8  665.05   292.9  666.71     303     671   313.1  677.23   323.2  685.94
   333.3  691.42     343  695.61   352.7  700.25   362.4  701.73   372.1  705.44
   391.5  717.71   401.2  723.22   449.6  747.97   459.3  751.75     469  752.76
#Mann= 3 , 0 , 0
    10.1      .1       0     138    .045       0     153      .1       0
Bank Sta=138,153
XS Rating Curve= 0 ,0
Exp/Cntr=0.3,0.1

Type RM Length L Ch R = 1 ,2801.5  ,148.1,147.6,146.7
XS GIS Cut Line= 2
      1572767.31      297641.101     1572920.701       298022.54
#Sta/Elev= 30
      10  667.98    20.1  666.17    30.1   665.1    40.1  664.91    80.2   661.8
   110.3  659.23   130.4  657.76     163  656.58   170.5  656.21     178  656.26
   180.5  656.28   190.5  659.42   200.5  665.88   210.6  673.47   230.6  688.12
   240.7  695.11   260.7  708.48   270.7  709.16   280.8  715.53   290.8  722.08
   300.8  727.64   310.9  732.77   320.9  737.64   330.9  741.51     351  748.66
     371  756.55     381  759.91   391.1     759   401.1  762.02   411.1  765.69
#Mann= 3 , 0 , 0
       0      .1       0     163    .045       0     178      .1       0
Bank Sta=163,178
XS Rating Curve= 0 ,0
Exp/Cntr=0.3,0.1

Type RM Length L Ch R = 1 ,2654    ,201.7,201.9,202.4
XS GIS Cut Line= 2
     1572589.826      297600.377     1572788.351      298060.548
#Sta/Elev= 30
      10  715.99    40.1  699.45    50.1  695.17    60.1  691.47    70.2  688.61
    90.2  679.03   110.3  670.19   120.3  665.39   130.3  661.84   140.3  660.56
   160.4  659.06   180.4  658.31   238.1 653.325   250.6  653.02   253.1  653.58
   260.6  655.26   270.6  660.65   280.7  666.97   290.7  670.43   300.7  672.47
   310.7   677.9   320.7  683.72   380.9  721.36   390.9  727.11   400.9  734.07
     411  739.23     421  741.74     441  754.62   451.1  760.87   501.2  791.25
#Mann= 3 , 0 , 0
      10      .1       0   238.1    .045       0   253.1      .1       0
Bank Sta=238.1,253.1
XS Rating Curve= 0 ,0
Exp/Cntr=0.3,0.1

Type RM Length L Ch R = 1 ,2452.1  ,234,244.7,255.4
XS GIS Cut Line= 2
     1572415.734      297696.755     1572604.418      298143.352
#Sta/Elev= 30
    10.1  694.74    20.2   687.2    30.3  682.55    40.4  680.08    60.6  665.28
    70.7  659.94    80.8  659.25     101  659.26   111.1  658.24   121.2  656.36
   131.3  655.16   141.4  654.67   161.6  654.31   234.9  650.96   242.4  650.51
   249.9  650.59   252.5  650.63   272.7  658.52   282.8  663.77   292.9  673.23
     303  681.11   323.2  694.42   333.3   700.7   343.4  706.44   383.8  726.55
   393.9  729.78     404  732.04   444.4  751.48   464.6  761.99   484.8  773.33
#Mann= 3 , 0 , 0
       0      .1       0   234.9    .045       0   249.9      .1       0
Bank Sta=234.9,249.9
XS Rating Curve= 0 ,0
Exp/Cntr=0.3,0.1

Type RM Length L Ch R = 1 ,2207.4  ,310,318.6,327.1
XS GIS Cut Line= 2
     1572303.067      297677.751     1572266.416      298215.296
#Sta/Elev= 30
      10  721.73      20  716.73    29.9  711.38    39.9  709.46    49.9  705.95
    59.9  700.63    99.8   680.4   129.7  664.42   139.7  661.77   149.7  660.35
   169.6   654.3   179.6  651.52   189.6  650.03   229.5  647.93   249.4  647.41
   307.8 644.575   319.3  644.44   322.8 645.149   329.3  646.46   339.2   650.3
   349.2  650.63   359.2  654.66   369.2   657.2   379.2  658.33     429  662.77
     439   664.6     449  664.78   468.9   668.5   528.8  677.89   538.8   679.8
#Mann= 3 , 0 , 0
      10     .06       0   307.8    .045       0   322.8      .1       0
Bank Sta=307.8,322.8
XS Rating Curve= 0 ,0
Exp/Cntr=0.3,0.1

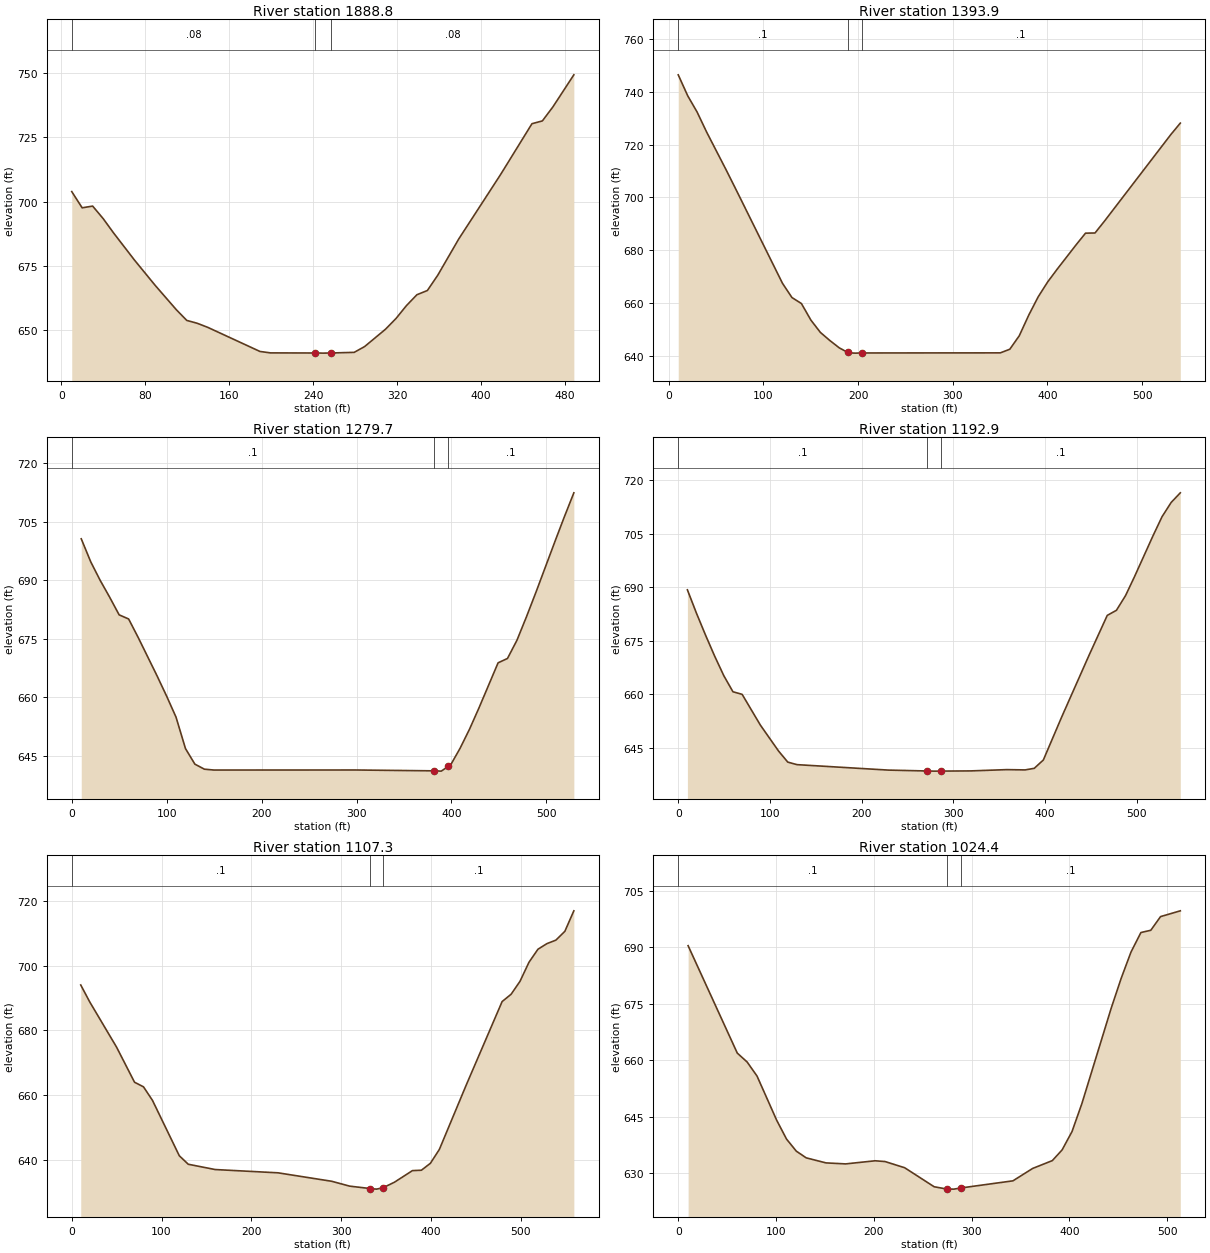
Type RM Length L Ch R = 1 ,1888.8  ,500.2,495,489.8
XS GIS Cut Line= 2
     1572101.149       297662.48     1571886.335      298101.271
#Sta/Elev= 30
      10  703.92    19.9  697.62    29.9  698.29    39.9  693.44    49.9  687.83
    69.8   677.3    89.7  667.39   109.7  658.01   119.6  653.87   129.6  652.75
   139.6  651.17   189.4   641.8   199.4  641.24   241.9   641.2  249.92  641.15
   256.9   641.2   279.2  641.45   289.1  643.68   309.1  650.45   319.1  654.62
     329   659.6     339  663.84     349  665.49   358.9  671.44   378.9  685.52
   418.8  710.57   448.7  730.31   458.6  731.39   468.6  736.82   488.6   749.3
#Mann= 3 , 0 , 0
      10     .08       0   241.9    .045       0   256.9     .08       0
Bank Sta=241.9,256.9
XS Rating Curve= 0 ,0
Exp/Cntr=0.3,0.1

Type RM Length L Ch R = 1 ,1393.9  ,115.6,114.2,112.7
XS GIS Cut Line= 2
     1571648.783      297384.545     1571522.542      297909.873
#Sta/Elev= 30
      10  746.38      20  738.47      30  732.26      40  724.73      60  710.85
      70  703.73   120.1  667.55   130.1  662.16   140.1   659.9   150.1  653.64
   160.1  648.99   170.1  645.92   180.1  643.13     189 641.403   190.1  641.19
   197.6  641.14     204   641.2   350.2  641.24   360.2  642.61   370.2   647.7
   380.2  655.49   390.2  662.44   400.2  668.06   410.2  672.86   430.2  682.08
   440.2  686.51   450.2  686.57   460.2  691.05   530.3   723.8   540.3  728.12
#Mann= 3 , 0 , 0
      10      .1       0     189    .045       0     204      .1       0
Bank Sta=189,204
XS Rating Curve= 0 ,0
Exp/Cntr=0.3,0.1

Type RM Length L Ch R = 1 ,1279.7  ,86.6,86.8,87
XS GIS Cut Line= 2
      1571518.47      297347.894     1571428.879       297869.15
#Sta/Elev= 30
      10   700.6      20  694.69    29.9  689.95    39.9  685.63    49.9  681.09
    59.9  680.03    69.9  675.32    89.8  665.46    99.8   660.3   109.8  654.86
   119.8  646.77   129.7  642.78   139.7  641.49   149.7  641.27   299.4  641.28
   381.7  641.06   389.2  640.99   396.7   642.2   399.2  642.61   409.1  646.87
   419.1   651.8   429.1  657.29   449.1  668.78     459   669.9     469  674.59
     479   680.6     489   686.9   508.9  699.86   518.9  706.24   528.9   712.4
#Mann= 3 , 0 , 0
       0      .1       0   381.7    .045       0   396.7      .1       0
Bank Sta=381.7,396.7
XS Rating Curve= 0 ,0
Exp/Cntr=0.3,0.1

Type RM Length L Ch R = 1 ,1192.9  ,87,85.6,84.9
XS GIS Cut Line= 2
     1571439.738      297319.388     1571342.003       297858.29
#Sta/Elev= 30
      10  689.29    19.9  682.72    29.9  676.51    39.8  670.65    49.8  665.15
    59.7  660.68    69.7  659.96    89.6  651.33   109.5  644.03   119.5  640.94
   129.5  640.23     229   638.7   271.3  638.45   278.8  638.41   286.3  638.42
   318.7  638.47   358.5  638.83   378.4  638.75   388.4   639.2   398.3  641.54
   418.2  653.54   448.1   670.9     468  682.11     478  683.54   487.9  687.64
   497.9  693.07   517.8  704.39   527.8  709.82   537.7   713.8   547.7  716.51
#Mann= 3 , 0 , 0
       0      .1       0   271.3    .045       0   286.3      .1       0
Bank Sta=271.3,286.3
XS Rating Curve= 0 ,0
Exp/Cntr=0.3,0.1

Type RM Length L Ch R = 1 ,1107.3  ,80.6,82.9,84.3
XS GIS Cut Line= 2
     1571350.147      297294.954     1571263.272      297847.431
#Sta/Elev= 30
      10  694.01      20  688.79    49.9  674.84    69.9  664.02    79.9  662.59
    89.9  658.42   119.8  641.33   129.8  638.71   159.8  637.08   229.7  636.07
   289.6  633.46   309.6  631.96   332.1  631.23   339.6  631.04   347.1  631.51
   359.5  633.18   379.5  636.75   389.5  636.87   399.5  639.01   409.5  643.29
   439.4  663.13   479.4  688.89   489.4  691.15   499.3  695.13   509.3     701
   519.3  705.03   529.3  706.76   539.3  707.84   549.3  710.56   559.3  716.88
#Mann= 3 , 0 , 0
       0      .1       0   332.1    .045       0   347.1      .1       0
Bank Sta=332.1,347.1
XS Rating Curve= 0 ,0
Exp/Cntr=0.3,0.1

Type RM Length L Ch R = 1 ,1024.4  ,107.8,112.4,117.2
XS GIS Cut Line= 2
     1571294.493      297300.384     1571187.255      297802.635
#Sta/Elev= 30
    10.1  690.43    60.4  661.94    70.5  659.57    80.6  655.85   100.7  644.13
   110.8  639.12   120.8  635.92   130.9  634.15   151.1  632.81   171.2  632.54
   201.4  633.37   211.5  633.17   231.6  631.53   261.8  626.48   274.5  625.88
     282  625.85   289.5  626.17   342.4  628.05   362.5  631.33   382.7  633.42
   392.7  636.26   402.8  641.11   412.9  648.53   443.1  674.01   453.2  681.84
   463.2  688.77   473.3  693.92   483.4  694.52   493.4  698.15   513.6  699.68
#Mann= 3 , 0 , 0
       0      .1       0   274.5    .045       0   289.5      .1       0
Bank Sta=274.5,289.5
XS Rating Curve= 0 ,0
Exp/Cntr=0.3,0.1

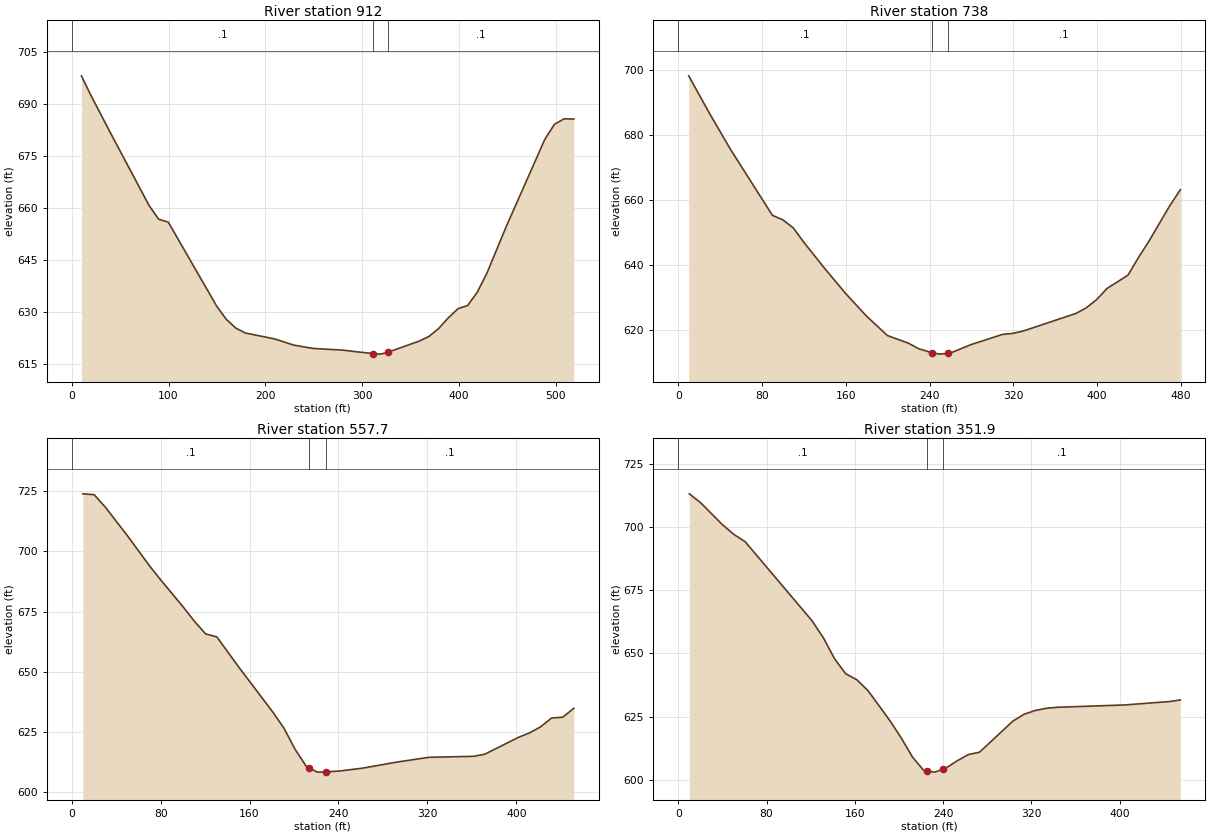
Type RM Length L Ch R = 1 ,912     ,174,174,174
XS GIS Cut Line= 2
     1571251.055       297275.95     1571046.082       297752.41
#Sta/Elev= 30
      10  698.22    19.9  692.51    39.9  681.78    79.8  660.79    89.8  656.78
    99.7  655.96   149.6  631.74   159.6  627.88   169.6  625.31   179.5  623.91
   209.5  622.22   229.4  620.42   249.4  619.46   279.3  618.99   311.7  617.95
   319.2  617.82   326.7  618.38   359.1  621.59   369.1  622.94     379  625.21
     389   628.3     399  630.95     409  631.86   418.9  635.69   428.9  641.21
   448.9  654.71   488.8  679.92   498.7  684.22   508.7  685.81   518.7  685.72
#Mann= 3 , 0 , 0
       0      .1       0   311.7    .045       0   326.7      .1       0
Bank Sta=311.7,326.7
XS Rating Curve= 0 ,0
Exp/Cntr=0.3,0.1

Type RM Length L Ch R = 1 ,738     ,181.6,180.3,179
XS GIS Cut Line= 2
     1571085.447      297240.657     1570891.334      297679.109
#Sta/Elev= 30
      10  698.26      30  686.62    49.9  675.62    89.9   655.3    99.9  653.89
   109.9   651.4   119.9  647.01   139.9   638.9   159.8  631.23   179.8  624.24
   199.8  618.24   219.8   615.9   229.8  614.16   242.2  612.97   249.7  612.52
   257.2  612.75   259.7  612.83   279.7  615.46   309.7  618.59   319.7  618.92
   329.7  619.66   379.6  625.03   389.6  626.75   399.6  629.32   409.6  632.77
   429.6  636.87   439.5  642.25   449.5  647.29   469.5  658.28   479.5  663.15
#Mann= 3 , 0 , 0
       0      .1       0   242.2    .045       0   257.2      .1       0
Bank Sta=242.2,257.2
XS Rating Curve= 0 ,0
Exp/Cntr=0.3,0.1

Type RM Length L Ch R = 1 ,557.7   ,206.1,205.8,205.5
XS GIS Cut Line= 2
     1570896.764      297194.504     1570739.301      297618.024
#Sta/Elev= 30
      10  723.88    20.1  723.53    30.1  718.41    50.2  706.43    70.3  693.79
    80.3  688.01   100.4  676.86   110.5  670.91   120.5  665.71   130.5  664.53
   150.6  651.77   180.7  633.44   190.8  626.73   200.8  617.98   210.9  610.85
   213.4  610.23   220.9  608.38   228.4  608.46     241  608.85   261.1  609.98
   291.2  612.44   321.3  614.53   361.5  614.94   371.5  615.78   401.6  622.74
   411.7  624.62   421.7  627.11   431.8  630.84   441.8  631.17   451.8  634.87
#Mann= 3 , 0 , 0
       0      .1       0   213.4    .045       0   228.4      .1       0
Bank Sta=213.4,228.4
XS Rating Curve= 0 ,0
Exp/Cntr=0.3,0.1

Type RM Length L Ch R = 1 ,351.9   ,351.5,351.9,352.2
XS GIS Cut Line= 2
     1570698.616      297129.725     1570545.425      297558.161
#Sta/Elev= 30
    10.1  713.14    20.2  709.67    40.4  700.79    50.6  697.04    60.7  694.17
   121.3   662.9   131.4  656.27   141.6  647.95   151.7  641.99   161.8  639.59
   171.9  635.33   192.1  623.24   202.2  616.48   212.3     609   222.4  603.73
   225.1  603.54   232.6  603.04   240.1  604.25   242.7  604.67   252.8  607.52
   262.9  609.98     273  610.92   303.3  623.23   313.4  625.93   323.6  627.45
   333.7   628.3   343.8   628.7   404.4  629.61   444.9  630.95     455  631.59
#Mann= 3 , 0 , 0
       0      .1       0   225.1    .045       0   240.1      .1       0
Bank Sta=225.1,240.1
XS Rating Curve= 0 ,0
Exp/Cntr=0.3,0.1

Chan Stop Cuts=-1
Use User Specified Reach Order=0